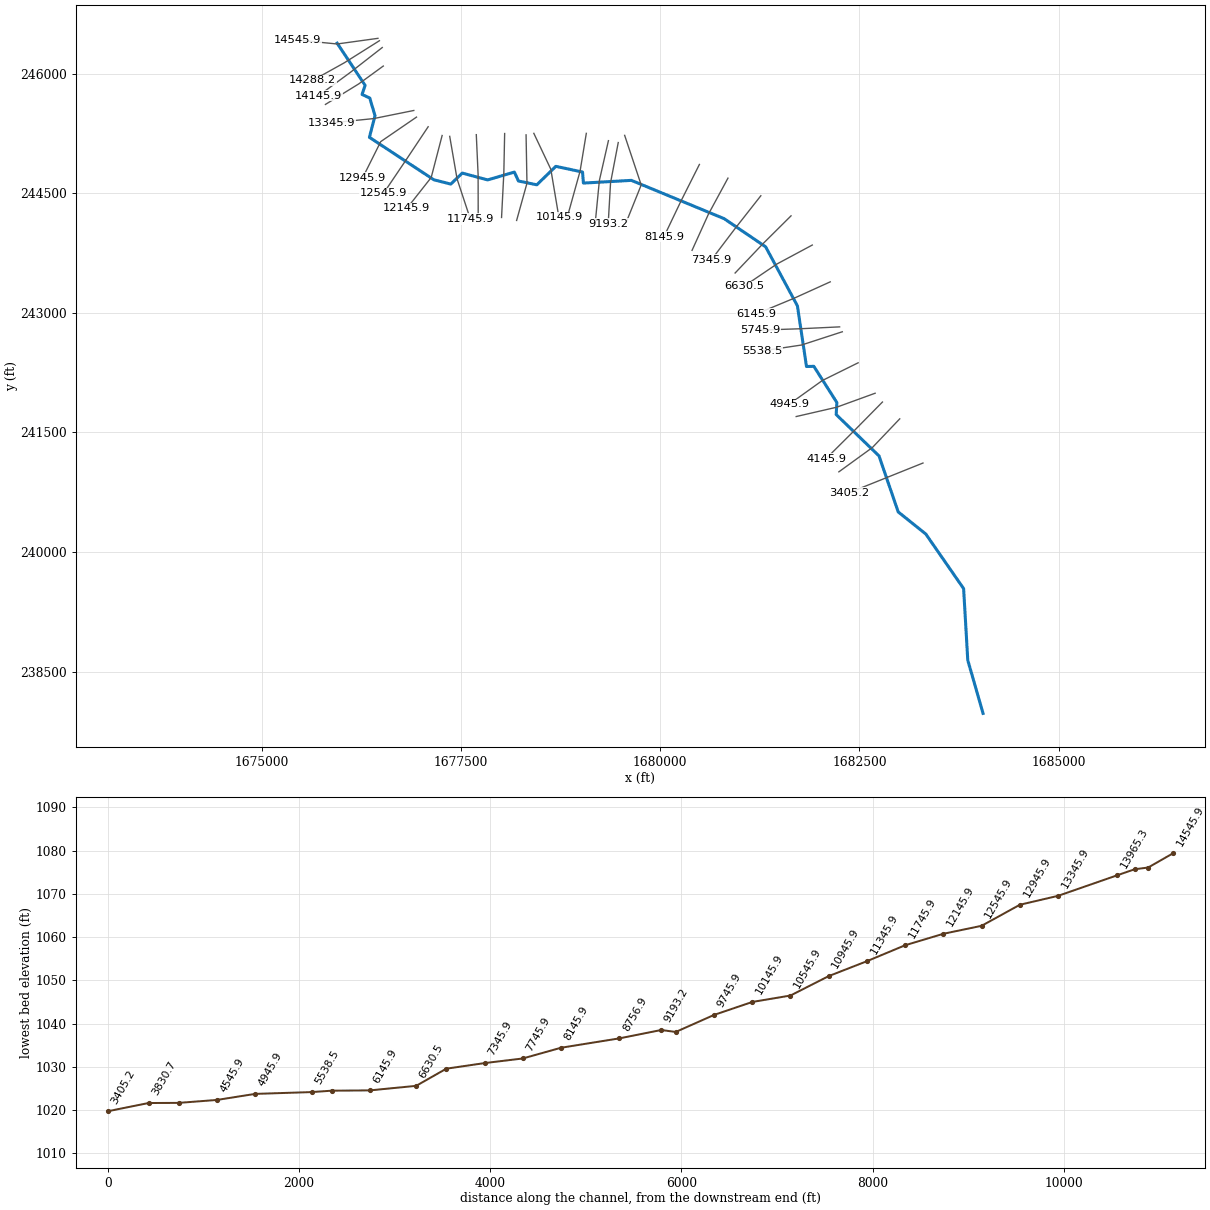
--- RghtFk.prj (project) ---

Proj Title=RghtFk
Current Plan=p01
Default Exp/Contr=0,0
English Units
Geom File=g01
Flow File=f01
Plan File=p01
BEGIN DESCRIPTION:
END DESCRIPTION:
DSS Export Rating Curves= 0
DSS Export Rating Curve Sorted= 0
DSS Export Volume Flow Curves= 0
DXF OffsetX= 0
DXF OffsetY= 0
DXF ScaleX= 0
DXF ScaleY= 0

--- RghtFk.p01 (plan) ---

Plan Title=Floodplain
Program Version=4.00
Geom File=g01
Flow File=f01
K Sum by GR=0
Std Step Tol=0.01
Critical Tol=0.01
Num of Std Step Trials=20
Max Error Tol=0.3
Flow Tol Ratio=0.001
Split Flow NTrial=30
Split Flow Tol=0.02
Split Flow Ratio=0.02
Log Output Level=0
Friction Slope Method=1
Unsteady Friction Slope Method=2
Unsteady Bridges Friction Slope Method=1
Global Log Level=0
CheckData=False
Run HTab=0
Run UNet=0
Run PostProcess=0
UNET Theta=0
UNET Theta Warmup=0
UNET ZTol=0
UNET ZSATol=0
UNET MxIter=0
UNET MaxInSteps=0
UNET DtIC=0
UNET DtMin=0
UNET MaxCRTS=0
UNET WFStab=0
UNET SFStab=0
UNET WFX=0
UNET SFX=0
UNET DSS MLevel=0
UNET DZMax Abort=0
UNET Convert EG Bridges=0
UNET Use Existing IB Tables=0
UNET Froude Limit=0
UNET Froude Power=0
Write IC File=0
Echo Input=False
Echo Output=False
Write Detailed=0

--- RghtFk.f01 (steady flow) ---

Flow Title=NFF Regression Equation
Program Version=4.00
Number of Profiles=1
Profile Names=P100yr
River Rch & RM=RghtFk,Main      ,14545.9
650.9672
River Rch & RM=RghtFk,Main      ,14288.2
650.9672
River Rch & RM=RghtFk,Main      ,14145.9
747.4272
River Rch & RM=RghtFk,Main      ,13345.9
772.2763
River Rch & RM=RghtFk,Main      ,12945.9
851.4480
River Rch & RM=RghtFk,Main      ,11745.9
918.6190
River Rch & RM=RghtFk,Main      ,8756.9
986.0567
River Rch & RM=RghtFk,Main      ,8145.9
1575.577
River Rch & RM=RghtFk,Main      ,6945.9
1620.427
River Rch & RM=RghtFk,Main      ,4945.9
1798.889
River Rch & RM=RghtFk,Main      ,209.6
1928.978
River Rch & RM=RghtFk,Main      ,30.4
1931.168
Boundary for River Rch & Prof#=RghtFk,Main      ,1
Up Type=0
Dn Type=3
Dn Slope=0.003389

--- RghtFk.g01 (geometry) ---

Geom Title=USGS 3m DEM
Program Version=4.00

River Reach=RghtFk     ,Main
Reach XY= 30
     1675944.963      246382.253     1676295.782      245853.605
     1676256.879      245739.521     1676353.936      245694.414
     1676420.032      245472.710     1676349.605      245201.657
     1677158.304      244669.359     1677371.159      244615.189
     1677515.116      244753.006     1677833.771      244667.687
     1678168.932      244765.818     1678220.150      244654.176
     1678450.474      244606.273     1678689.517      244837.643
     1679024.329      244766.435     1679035.732      244627.833
     1679637.676      244661.929     1680801.569      244181.782
     1681322.667      243828.536     1681721.098      243089.165
     1681835.457      242327.515     1681927.489      242329.784
     1682216.497      241875.871     1682208.083      241724.558
     1682745.515      241206.378     1682986.342      240504.341
     1683332.673      240226.681     1683807.360      239542.160
     1683859.514      238644.172     1684051.250      237977.418

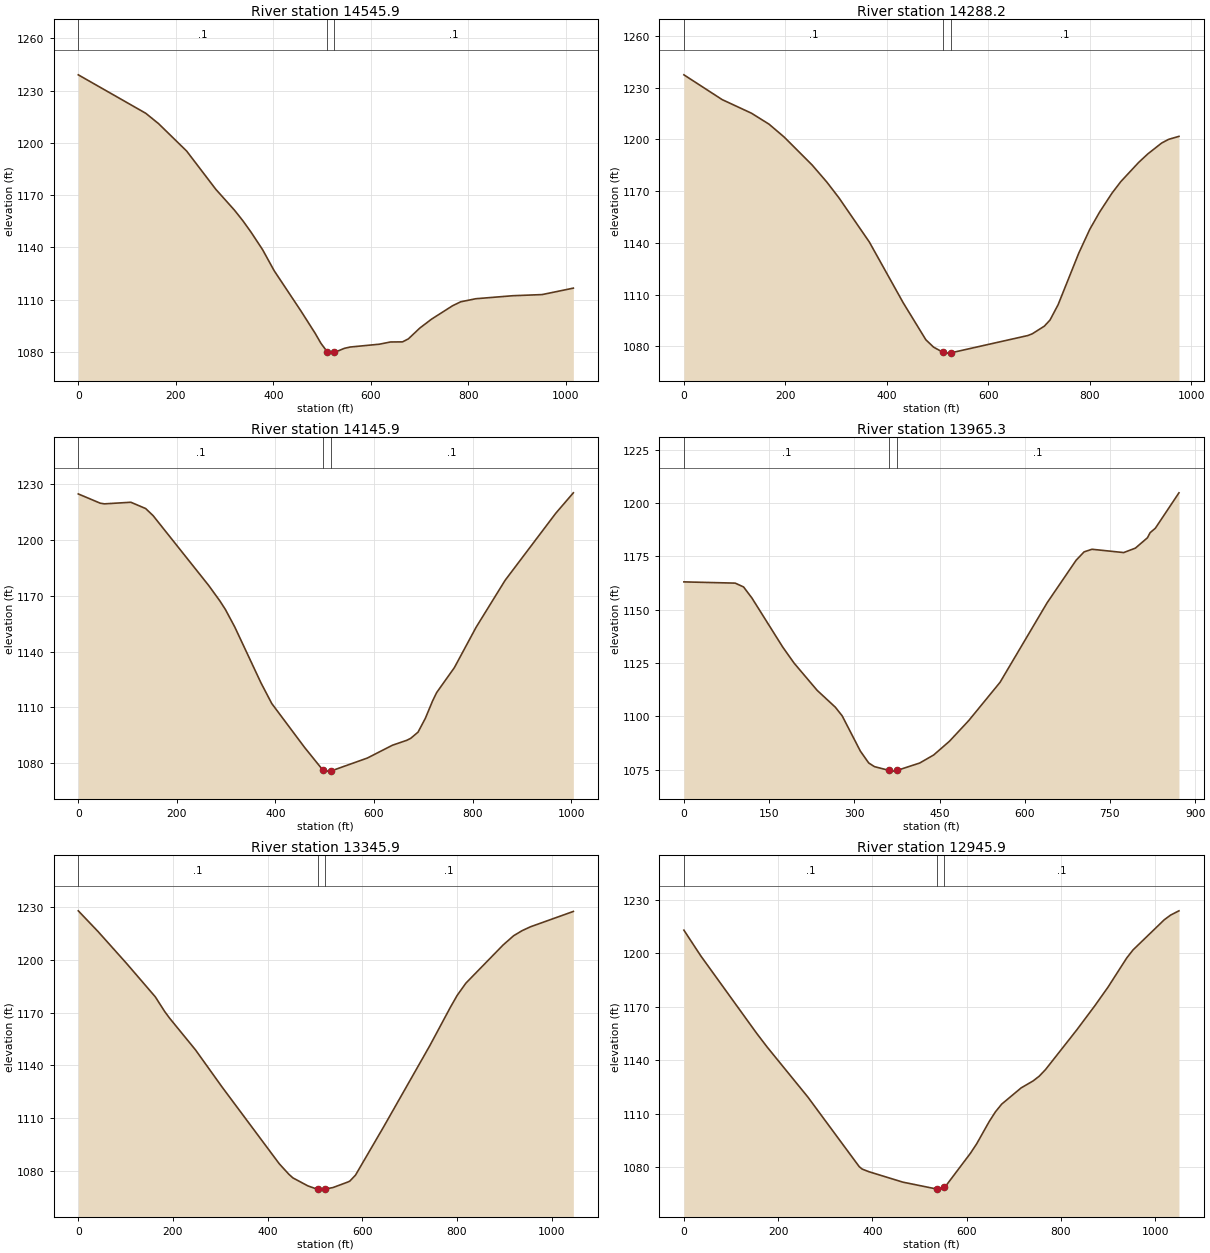
Type RM Length L Ch R = 1 ,14545.9,248.243,257.71,271.411
XS GIS Cut Line= 3
     1676456.940      246443.174     1675943.977      246372.302
     1675448.961      246421.356
#Sta/Elev= 30
       0 1239.08   138.3 1217.02   164.4 1211.12   222.2 1195.34   282.1 1173.36
   320.4 1161.38   337.9 1155.20   354.0 1148.91   378.0 1138.73   401.9 1126.58
   457.3 1103.27   485.8 1090.74   497.8 1084.92   510.3 1080.25   521.8 1079.36
   525.3 1079.73   545.6 1082.10   557.6 1082.86   617.2 1084.47   640.4 1085.76
   664.9 1085.82   676.9 1087.53   700.7 1093.81   724.6 1098.88   767.6 1106.55
   784.2 1108.81   815.3 1110.58   891.6 1112.31   951.3 1112.96  1015.3 1116.66
#Mann= 3 , 0 , 0
       0     0.1       0   510.3   0.045       0   525.3     0.1       0
Bank Sta=   510.3,   525.3
Exp/Cntr=0.3,0.1

Type RM Length L Ch R = 1 ,14288.2,140.025,142.29,145.086
XS GIS Cut Line= 3
     1676475.160      246413.346     1676036.813      246137.654
     1675637.154      245914.922
#Sta/Elev= 30
       0 1237.41    75.4 1223.04   133.0 1215.18   167.5 1208.86   197.3 1201.41
   252.8 1185.09   281.5 1175.29   305.3 1166.19   365.3 1140.53   432.2 1105.23
   476.8 1083.81   491.9 1079.58   510.7 1076.53   519.9 1076.10   525.7 1076.24
   677.6 1086.29   686.4 1087.30   710.2 1091.74   721.3 1095.26   737.3 1104.17
   778.1 1134.12   799.8 1147.92   818.9 1157.77   843.5 1168.84   860.9 1175.54
   895.8 1186.57   914.0 1191.56   941.2 1197.85   954.8 1199.98   975.4 1201.75
#Mann= 3 , 0 , 0
       0     0.1       0   510.7   0.045       0   525.7     0.1       0
Bank Sta=   510.7,   525.7
Exp/Cntr=0.3,0.1

Type RM Length L Ch R = 1 ,14145.9,181.338,180.596,179.603
XS GIS Cut Line= 3
     1676510.995      246327.873     1676112.750      246017.910
     1675709.749      245722.425
#Sta/Elev= 30
       0 1224.75    44.6 1219.77    53.1 1219.42   106.6 1220.28   136.7 1216.90
   151.8 1213.08   264.6 1175.52   287.2 1167.25   298.4 1162.64   317.3 1153.30
   370.8 1123.07   392.5 1112.06   459.1 1088.44   493.0 1077.31   497.2 1076.54
   506.2 1075.69   512.2 1075.71   586.5 1082.73   637.3 1089.61   666.8 1092.30
   674.6 1093.36   689.3 1096.64   704.1 1104.07   718.8 1113.43   727.0 1117.90
   763.0 1131.34   807.1 1153.05   866.0 1178.31   968.6 1214.31  1004.4 1225.35
#Mann= 3 , 0 , 0
       0     0.1       0   497.2   0.045       0   512.2     0.1       0
Bank Sta=   497.2,   512.2
Exp/Cntr=0.3,0.1

Type RM Length L Ch R = 1 ,13965.3,577.746,619.404,599.225
XS GIS Cut Line= 3
     1676523.618      246095.658     1676216.823      245872.370
     1675797.808      245614.355
#Sta/Elev= 30
       0 1163.03    90.3 1162.45   105.0 1160.66   119.7 1155.48   174.0 1132.46
   194.2 1124.87   234.5 1112.20   266.5 1104.30   278.6 1100.24   310.6 1083.71
   325.3 1078.15   335.4 1076.42   360.7 1074.68   369.3 1074.31   375.7 1074.68
   415.1 1078.11   439.6 1081.86   467.4 1088.30   501.4 1098.00   556.5 1115.93
   639.4 1153.23   690.5 1173.19   704.5 1177.10   718.4 1178.32   774.2 1176.77
   794.8 1178.85   816.0 1183.70   820.7 1186.09   830.0 1188.20   871.5 1204.78
#Mann= 3 , 0 , 0
       0     0.1       0   360.7   0.045       0   375.7     0.1       0
Bank Sta=   360.7,   375.7
Exp/Cntr=0.3,0.1

Type RM Length L Ch R = 1 ,13345.9,394.502,400,421.773
XS GIS Cut Line= 3
     1676906.868      245538.363     1676403.134      245436.839
     1675874.010      245383.103
#Sta/Elev= 30
       0 1227.98    41.6 1216.23   102.0 1198.03   162.5 1179.07   182.6 1170.62
   192.7 1166.93   247.5 1148.85   303.6 1127.72   424.5 1083.99   444.7 1078.04
   453.3 1075.95   485.0 1071.39   501.8 1069.79   506.4 1069.77   513.9 1069.55
   521.4 1069.62   537.8 1070.43   569.5 1073.60   573.6 1074.13   585.5 1077.51
   645.0 1105.01   742.9 1151.41   786.2 1173.18   800.3 1179.84   818.7 1186.80
   897.3 1208.52   919.6 1213.81   937.9 1216.75   955.5 1218.93  1045.7 1227.63
#Mann= 3 , 0 , 0
       0     0.1       0   506.4   0.045       0   521.4     0.1       0
Bank Sta=   506.4,   521.4
Exp/Cntr=0.3,0.1

Type RM Length L Ch R = 1 ,12945.9,390.497,400,396.149
XS GIS Cut Line= 3
     1676940.768      245455.453     1676491.662      245147.974
     1676265.275      244695.082
#Sta/Elev= 30
       0 1213.11    35.8 1198.66   153.6 1155.40   176.8 1147.34   263.1 1119.25
   372.0 1080.15   378.2 1078.78   392.6 1077.28   464.6 1071.42   536.8 1067.53
   540.2 1067.49   551.8 1068.55   556.5 1069.52   608.0 1087.63   621.3 1092.96
   647.9 1105.49   661.1 1110.94   674.4 1115.29   715.8 1124.44   740.8 1128.28
   754.0 1130.98   767.3 1134.67   833.7 1157.01   871.9 1170.54   900.1 1181.09
   939.9 1197.52   953.1 1201.99  1019.5 1218.97  1032.8 1221.57  1050.6 1223.98
#Mann= 3 , 0 , 0
       0     0.1       0   536.8   0.045       0   551.8     0.1       0
Bank Sta=   536.8,   551.8
Exp/Cntr=0.3,0.1

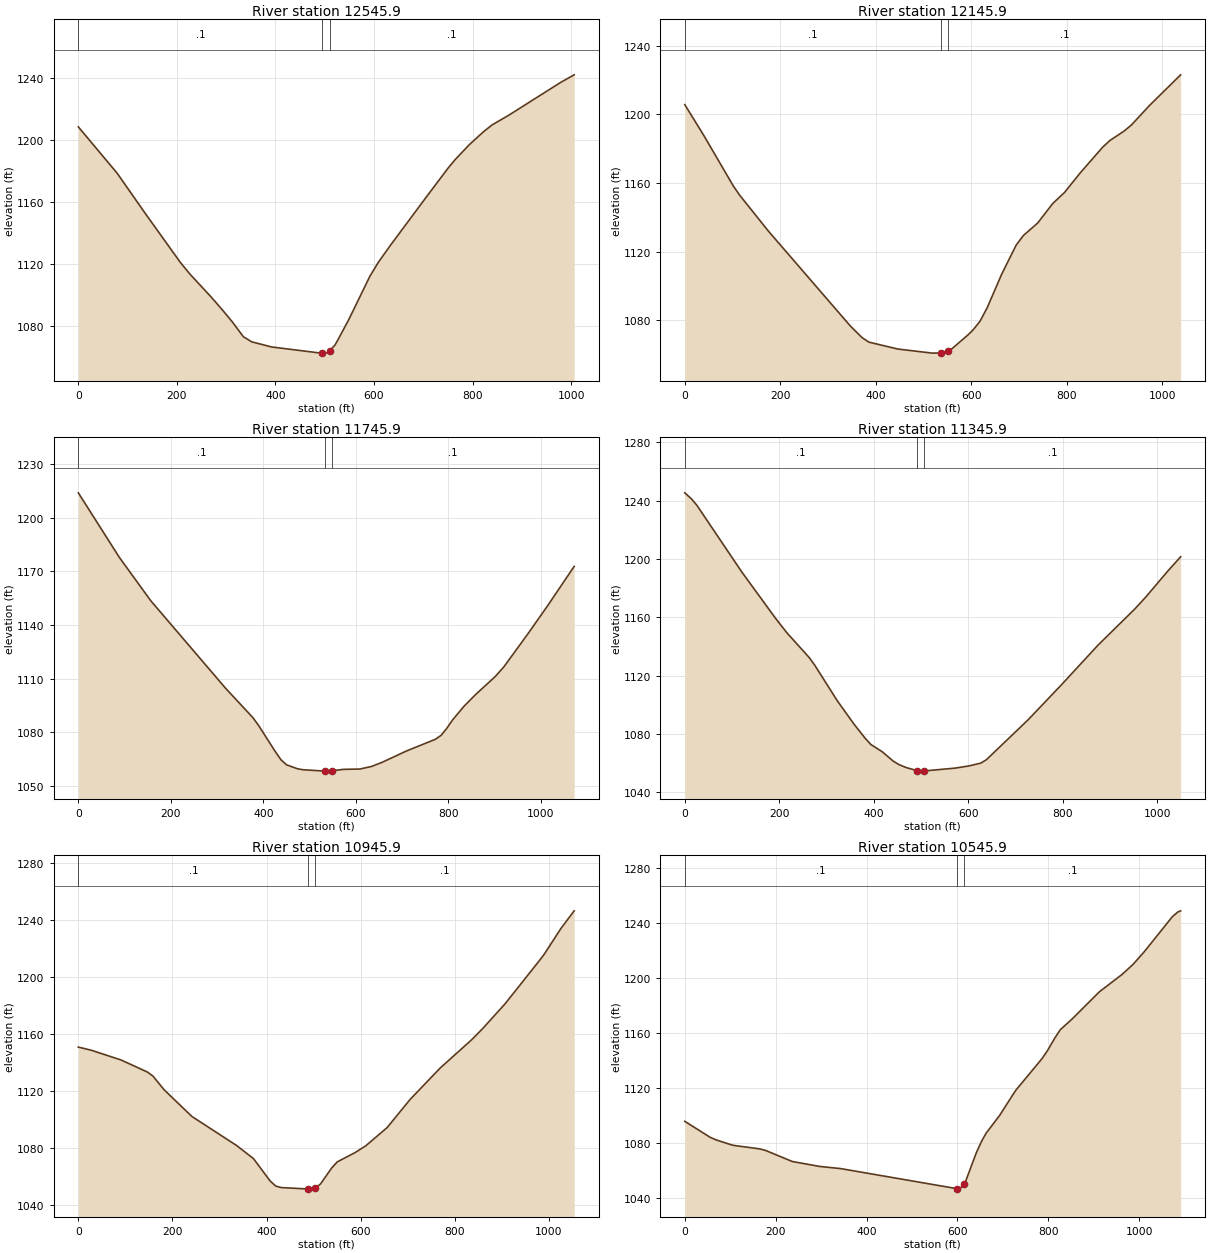
Type RM Length L Ch R = 1 ,12545.9,391.138,400,398.4
XS GIS Cut Line= 3
     1677087.013      245334.424     1676808.265      244915.990
     1676526.544      244498.827
#Sta/Elev= 30
       0 1208.33    78.6 1178.55   135.6 1152.69   207.0 1121.05   227.1 1113.29
   269.9 1098.65   292.6 1090.35   312.8 1082.64   334.9 1073.19   352.0 1069.88
   392.4 1066.58   492.3 1062.62   495.3 1062.65   506.6 1062.84   510.3 1064.21
   520.9 1067.88   526.7 1071.12   548.9 1084.26   591.6 1112.09   608.7 1121.04
   632.7 1131.77   707.1 1163.53   750.1 1181.64   764.4 1187.12   793.1 1196.75
   821.7 1205.04   839.6 1209.56   873.8 1215.88   979.3 1237.04  1006.2 1241.83
#Mann= 3 , 0 , 0
       0     0.1       0   495.3   0.045       0   510.3     0.1       0
Bank Sta=   495.3,   510.3
Exp/Cntr=0.3,0.1

Type RM Length L Ch R = 1 ,12145.9,386.207,400,420.286
XS GIS Cut Line= 3
     1677262.308      245224.706     1677125.024      244697.714
     1676818.989      244309.675
#Sta/Elev= 30
       0 1205.61    40.1 1187.54   101.4 1158.33   114.4 1153.04   175.0 1131.96
   346.7 1076.64   371.3 1069.84   385.8 1067.18   446.3 1063.17   518.6 1060.78
   537.1 1060.89   552.1 1062.21   558.8 1063.12   592.6 1071.23   603.2 1074.08
   618.4 1079.30   633.5 1087.21   663.7 1106.66   694.2 1123.71   709.1 1129.26
   739.3 1136.61   770.9 1148.00   795.5 1154.41   828.4 1165.81   875.4 1180.80
   890.5 1184.68   920.8 1190.30   935.9 1193.80   973.1 1205.00  1038.8 1222.99
#Mann= 3 , 0 , 0
       0     0.1       0   537.1   0.045       0   552.1     0.1       0
Bank Sta=   537.1,   552.1
Exp/Cntr=0.3,0.1

Type RM Length L Ch R = 1 ,11745.9,378.81,400,391.805
XS GIS Cut Line= 3
     1677357.540      245213.824     1677449.739      244680.459
     1677616.321      244176.898
#Sta/Elev= 30
       0 1214.02    88.6 1177.88   156.5 1153.60   318.0 1104.64   377.7 1087.98
   390.0 1083.57   425.9 1069.01   438.0 1064.50   450.0 1061.66   474.1 1059.42
   486.2 1058.89   533.8 1058.14   541.3 1058.13   548.8 1058.35   573.2 1059.13
   608.2 1059.29   634.1 1060.77   656.6 1063.06   709.2 1069.41   771.7 1075.96
   784.2 1078.20   796.7 1082.22   809.2 1086.90   834.2 1094.63   859.2 1101.16
   900.9 1111.05   919.7 1116.52   971.8 1135.07  1013.7 1150.52  1071.7 1172.80
#Mann= 3 , 0 , 0
       0     0.1       0   533.8   0.045       0   548.8     0.1       0
Bank Sta=   533.8,   548.8
Exp/Cntr=0.3,0.1

Type RM Length L Ch R = 1 ,11345.9,397.368,400,400.854
XS GIS Cut Line= 3
     1677691.107      245235.295     1677713.841      244736.067
     1677715.136      244186.176
#Sta/Elev= 30
       0 1245.37    13.8 1241.30    25.7 1236.78   120.7 1191.05   192.0 1159.34
   215.8 1149.48   263.4 1132.35   275.2 1127.06   322.8 1102.73   358.4 1086.59
   382.2 1076.86   394.1 1072.66   417.9 1067.75   441.6 1061.21   453.5 1058.92
   468.7 1056.87   492.2 1054.73   501.1 1054.44   507.2 1054.57   572.3 1056.51
   601.0 1057.97   626.6 1059.94   638.4 1062.26   726.6 1089.60   797.9 1113.87
   874.7 1140.87   952.2 1165.54   976.0 1173.92  1023.4 1192.06  1049.6 1201.47
#Mann= 3 , 0 , 0
       0     0.1       0   492.2   0.045       0   507.2     0.1       0
Bank Sta=   492.2,   507.2
Exp/Cntr=0.3,0.1

Type RM Length L Ch R = 1 ,10945.9,397.477,400,393.749
XS GIS Cut Line= 3
     1678046.970      245249.499     1678036.678      244753.372
     1678008.103      244196.288
#Sta/Elev= 30
       0 1150.81    28.0 1148.56    90.9 1141.74   146.7 1133.30   158.6 1130.45
   182.3 1120.85   241.3 1102.09   336.7 1081.59   372.3 1072.44   408.0 1056.62
   419.8 1053.11   431.7 1052.06   488.7 1051.09   491.1 1050.99   503.7 1051.66
   514.9 1054.66   538.6 1065.87   550.5 1070.14   588.5 1076.71   611.1 1081.46
   656.4 1094.23   705.1 1113.96   769.4 1136.16   835.9 1155.90   859.6 1163.85
   907.2 1181.25   978.5 1210.93   990.4 1216.05  1026.1 1234.28  1054.0 1246.57
#Mann= 3 , 0 , 0
       0     0.1       0   488.7   0.045       0   503.7     0.1       0
Bank Sta=   488.7,   503.7
Exp/Cntr=0.3,0.1

Type RM Length L Ch R = 1 ,10545.9,394.49,400,392.297
XS GIS Cut Line= 3
     1678315.847      245232.564     1678327.055      244625.761
     1678197.153      244159.203
#Sta/Elev= 30
       0 1095.83    56.2 1084.13    70.4 1082.14   106.0 1078.39   165.4 1075.75
   177.3 1074.71   236.6 1066.60   296.0 1063.05   343.5 1061.41   599.4 1046.81
   604.8 1046.50   614.4 1050.23   617.0 1051.27   641.7 1073.08   653.8 1081.77
   663.5 1087.36   692.4 1099.91   727.9 1118.19   786.2 1141.46   798.4 1147.38
   814.2 1156.36   826.5 1162.52   851.2 1169.90   912.8 1190.18   962.1 1202.63
   986.7 1210.06  1011.4 1219.31  1073.0 1244.72  1085.3 1248.18  1091.2 1248.97
#Mann= 3 , 0 , 0
       0     0.1       0   599.4   0.045       0   614.4     0.1       0
Bank Sta=   599.4,   614.4
Exp/Cntr=0.3,0.1

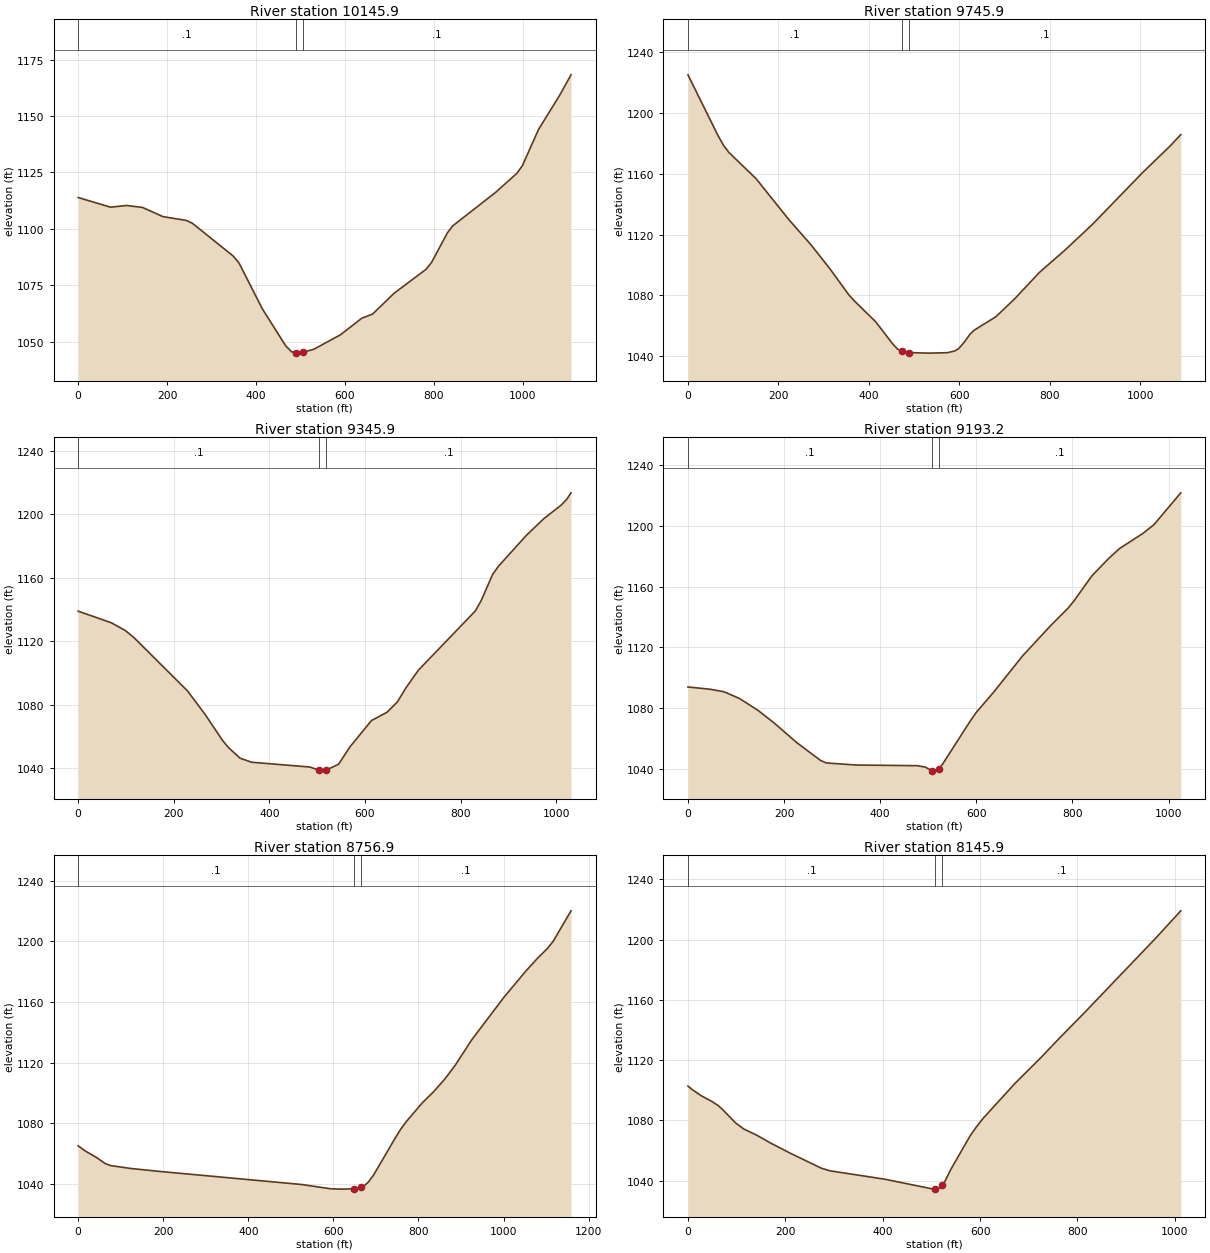
Type RM Length L Ch R = 1 ,10145.9,411.032,400,406.143
XS GIS Cut Line= 3
     1678413.219      245251.677     1678626.459      244801.505
     1678727.832      244199.561
#Sta/Elev= 30
       0 1113.92    72.8 1109.62   109.0 1110.39   144.7 1109.51   191.0 1105.43
   243.5 1103.75   256.7 1102.54   348.6 1088.02   361.8 1084.92   414.3 1064.60
   466.9 1048.22   480.0 1045.61   490.6 1045.08   492.4 1045.01   505.6 1045.43
   529.7 1046.69   589.9 1053.12   638.0 1060.48   662.1 1062.27   710.3 1071.47
   782.5 1082.13   794.6 1085.10   830.7 1098.33   842.7 1101.39   939.0 1116.19
   987.2 1124.71   999.2 1128.03  1035.4 1144.01  1083.5 1159.34  1108.5 1168.23
#Mann= 3 , 0 , 0
       0     0.1       0   490.6   0.045       0   505.6     0.1       0
Bank Sta=   490.6,   505.6
Exp/Cntr=0.3,0.1

Type RM Length L Ch R = 1 ,9745.9,399.044,400,404.145
XS GIS Cut Line= 3
     1679071.932      245251.578     1678993.515      244776.612
     1678830.024      244190.315
#Sta/Elev= 30
       0 1224.98    66.5 1185.03    78.6 1178.68    90.6 1173.95   150.8 1156.66
   223.0 1129.85   271.8 1113.36   313.4 1097.72   355.3 1080.55   367.4 1076.55
   415.5 1062.55   451.6 1048.55   463.6 1044.67   473.9 1043.10   488.9 1042.36
   533.7 1042.01   574.1 1042.30   589.8 1043.41   598.8 1044.98   611.1 1049.19
   623.4 1054.26   632.8 1057.04   681.0 1065.91   722.1 1077.54   777.4 1095.07
   833.0 1109.48   894.6 1126.63  1005.5 1160.67  1067.2 1178.38  1090.1 1185.68
#Mann= 3 , 0 , 0
       0     0.1       0   473.9   0.045       0   488.9     0.1       0
Bank Sta=   473.9,   488.9
Exp/Cntr=0.3,0.1

Type RM Length L Ch R = 1 ,9345.9,151.73,152.673,153.612
XS GIS Cut Line= 3
     1679349.573      245159.790     1679236.061      244661.108
     1679185.281      244144.026
#Sta/Elev= 30
       0 1138.84    69.2 1131.55    98.9 1126.59   116.3 1122.31   228.9 1088.55
   265.4 1073.87   302.0 1057.44   314.1 1053.03   338.5 1046.26   362.8 1043.69
   484.6 1040.67   503.9 1038.68   509.0 1038.08   518.9 1038.73   544.8 1042.45
   568.7 1053.41   613.6 1069.94   646.2 1075.19   668.0 1081.76   685.8 1090.59
   711.8 1101.68   830.9 1138.99   843.0 1145.45   866.9 1161.89   878.8 1166.99
   937.2 1186.45   974.3 1197.16  1010.1 1205.54  1022.0 1209.26  1031.0 1213.38
#Mann= 3 , 0 , 0
       0     0.1       0   503.9   0.045       0   518.9     0.1       0
Bank Sta=   503.9,   518.9
Exp/Cntr=0.3,0.1

Type RM Length L Ch R = 1 ,9193.2,418.575,436.326,416.733
XS GIS Cut Line= 3
     1679472.620      245136.316     1679376.241      244631.950
     1679346.734      244120.913
#Sta/Elev= 30
       0 1093.96    46.2 1092.46    74.7 1090.83   106.6 1086.48   145.7 1078.58
   179.2 1070.27   227.5 1057.05   275.9 1045.57   287.8 1043.93   350.3 1042.54
   476.8 1042.12   493.4 1041.22   507.5 1038.90   511.1 1038.53   517.5 1038.65
   522.5 1040.22   529.4 1042.95   588.2 1071.94   600.8 1077.56   636.5 1090.70
   695.9 1114.30   755.4 1134.62   791.1 1145.95   803.0 1150.58   840.6 1167.19
   874.3 1178.25   898.1 1185.17   945.7 1194.91   969.5 1200.82  1025.4 1221.83
#Mann= 3 , 0 , 0
       0     0.1       0   507.5   0.045       0   522.5     0.1       0
Bank Sta=   507.5,   522.5
Exp/Cntr=0.3,0.1

Type RM Length L Ch R = 1 ,8756.9,628.304,611.001,588.476
XS GIS Cut Line= 3
     1679553.084      245226.407     1679760.953      244604.186
     1679573.422      244137.786
#Sta/Elev= 30
       0 1065.15    17.6 1061.59    42.7 1057.53    63.1 1053.54    76.0 1052.13
   122.9 1050.24   188.6 1048.35   526.3 1039.62   593.5 1036.83   618.5 1036.60
   649.1 1036.79   656.0 1036.86   664.1 1037.70   672.7 1038.85   681.6 1041.04
   694.4 1045.83   745.6 1070.36   758.4 1076.14   771.2 1081.03   809.5 1093.59
   835.2 1100.66   860.8 1108.74   886.4 1118.22   924.8 1134.82  1001.2 1163.11
  1052.7 1180.38  1078.3 1188.26  1103.9 1195.42  1116.7 1199.89  1158.7 1220.03
#Mann= 3 , 0 , 0
       0     0.1       0   649.1   0.045       0   664.1     0.1       0
Bank Sta=   649.1,   664.1
Exp/Cntr=0.3,0.1

Type RM Length L Ch R = 1 ,8145.9,401.406,400,399.746
XS GIS Cut Line= 3
     1680491.258      244861.413     1680260.086      244402.378
     1680045.242      243952.966
#Sta/Elev= 30
       0 1102.86     8.8 1100.51    26.5 1096.55    48.8 1092.71    61.6 1090.01
    70.7 1087.41    97.3 1078.56   114.4 1074.38   141.5 1070.20   168.4 1065.25
   208.3 1058.58   274.1 1048.29   291.8 1046.59   404.8 1040.99   500.7 1034.66
   506.5 1034.54   512.8 1034.43   514.0 1034.56   521.5 1037.35   527.2 1039.24
   540.3 1047.78   579.8 1069.99   592.8 1075.93   606.1 1081.39   671.9 1104.71
   724.6 1121.67   764.0 1135.01   816.7 1152.36   961.4 1201.29  1012.1 1219.17
#Mann= 3 , 0 , 0
       0     0.1       0   506.5   0.045       0   521.5     0.1       0
Bank Sta=   506.5,   521.5
Exp/Cntr=0.3,0.1

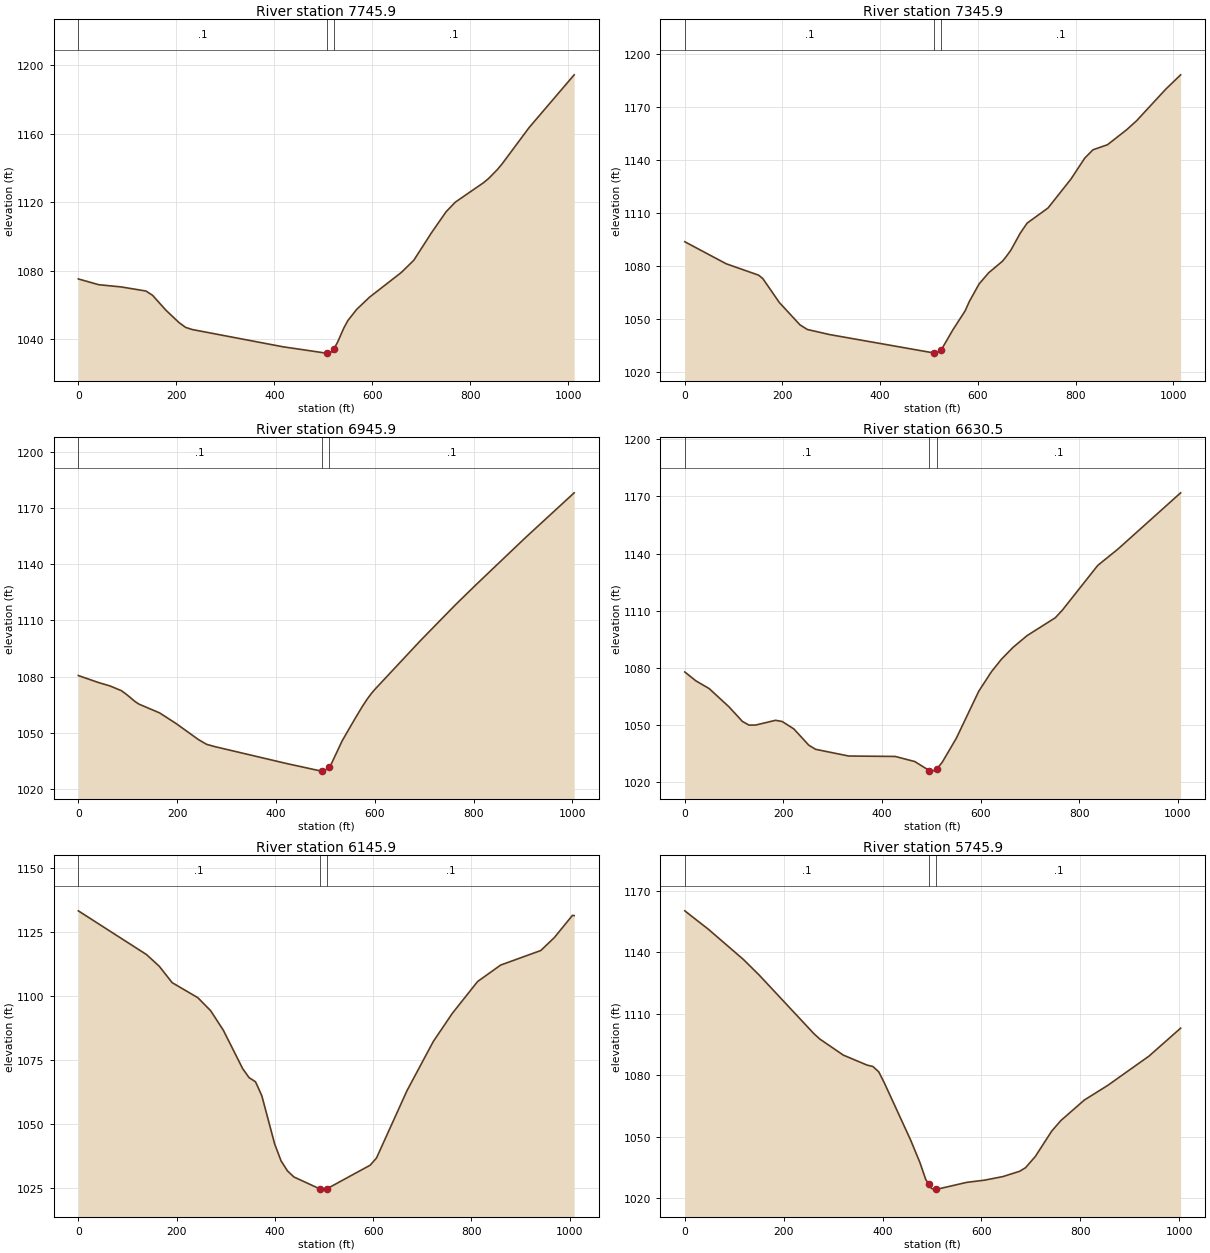
Type RM Length L Ch R = 1 ,7745.9,403.783,400,395.01
XS GIS Cut Line= 3
     1680849.655      244689.889     1680604.499      244237.691
     1680399.071      243784.303
#Sta/Elev= 30
       0 1075.23    41.5 1071.87    87.7 1070.56   138.0 1068.18   151.5 1065.69
   178.5 1057.08   205.6 1049.75   219.1 1046.95   232.6 1045.71   418.1 1035.63
   505.7 1031.95   506.9 1032.00   516.1 1032.58   521.9 1034.57   529.1 1038.28
   542.2 1046.76   550.3 1051.00   568.2 1057.47   594.3 1064.56   659.5 1079.05
   684.9 1086.17   720.7 1102.08   750.7 1114.42   769.6 1120.04   827.2 1131.38
   837.4 1133.79   855.0 1138.93   864.3 1142.07   920.2 1163.54  1012.1 1194.29
#Mann= 3 , 0 , 0
       0     0.1       0   506.9   0.045       0   521.9     0.1       0
Bank Sta=   506.9,   521.9
Exp/Cntr=0.3,0.1

Type RM Length L Ch R = 1 ,7345.9,402.735,400,397.506
XS GIS Cut Line= 3
     1681262.342      244468.865     1680942.251      244062.080
     1680641.747      243665.618
#Sta/Elev= 30
       0 1093.94    84.7 1081.47   151.2 1075.01   159.7 1073.10   193.5 1059.56
   235.8 1046.89   250.9 1044.26   296.2 1041.40   510.1 1030.97   514.8 1030.88
   525.1 1032.75   548.7 1044.01   574.1 1054.89   582.3 1059.99   602.5 1070.04
   622.2 1076.39   650.4 1082.92   656.8 1085.11   667.3 1089.05   686.6 1098.71
   700.8 1104.47   743.6 1113.04   790.9 1129.54   818.7 1141.24   835.6 1145.98
   865.4 1148.86   904.6 1157.34   925.0 1162.45   984.5 1180.26  1015.1 1188.43
#Mann= 3 , 0 , 0
       0     0.1       0   510.1   0.045       0   525.1     0.1       0
Bank Sta=   510.1,   525.1
Exp/Cntr=0.3,0.1

Type RM Length L Ch R = 1 ,6945.9,321.85,315.469,310.876
XS GIS Cut Line= 3
     1681641.383      244217.136     1681286.518      243864.962
     1680939.441      243500.087
#Sta/Elev= 30
       0 1080.61    40.5 1076.91    63.9 1075.08    87.1 1072.55    97.5 1070.55
   114.2 1066.86   122.6 1065.37   164.6 1060.66   198.2 1054.94   242.7 1046.50
   259.6 1043.90   276.4 1042.66   421.6 1033.64   492.0 1029.59   492.5 1029.61
   495.6 1029.70   505.4 1031.04   507.5 1031.81   512.1 1033.49   534.0 1045.79
   559.2 1057.26   574.3 1063.89   584.4 1067.96   594.0 1071.35   601.2 1073.52
   692.3 1099.23   763.8 1118.54   807.0 1129.62   905.3 1154.32  1003.5 1178.15
#Mann= 3 , 0 , 0
       0     0.1       0   492.5   0.045       0   507.5     0.1       0
Bank Sta=   492.5,   507.5
Exp/Cntr=0.3,0.1

Type RM Length L Ch R = 1 ,6630.5,486.3,484.531,479.627
XS GIS Cut Line= 3
     1681908.071      243850.885     1681462.342      243611.995
     1681048.672      243331.892
#Sta/Elev= 30
       0 1077.75    22.5 1073.07    49.4 1069.02    89.3 1059.50   116.8 1051.75
   130.2 1049.81   143.7 1049.85   184.1 1052.34   197.6 1051.70   221.2 1047.79
   251.5 1039.24   265.2 1037.09   332.3 1033.56   426.6 1033.34   466.3 1030.66
   495.8 1025.90   501.8 1025.62   510.8 1026.66   521.9 1030.27   550.5 1042.89
   596.0 1067.61   621.6 1077.83   641.9 1084.42   665.2 1090.61   693.9 1096.84
   751.3 1106.27   765.6 1110.27   837.3 1133.77   878.1 1142.32  1005.3 1171.92
#Mann= 3 , 0 , 0
       0     0.1       0   495.8   0.045       0   510.8     0.1       0
Bank Sta=   495.8,   510.8
Exp/Cntr=0.3,0.1

Type RM Length L Ch R = 1 ,6145.9,408.62,400,391.763
XS GIS Cut Line= 3
     1682133.432      243389.311     1681679.345      243183.567
     1681208.138      242987.448
#Sta/Elev= 30
       0 1133.12   138.8 1116.05   164.9 1111.46   191.0 1105.09   243.1 1099.25
   269.2 1094.18   295.2 1086.50   334.3 1071.60   347.4 1068.07   360.4 1066.46
   364.7 1064.71   373.4 1060.97   399.5 1042.20   412.5 1035.60   425.6 1031.68
   438.6 1029.32     491 1024.70   503.7 1024.57     506 1024.73   593.7 1033.89
   606.6 1036.67   668.8 1062.99   722.3 1082.16   760.9 1093.11   812.4 1105.54
   859.5 1111.98   941.0 1117.64   968.5 1122.67  1005.3 1131.33  1008.9 1131.27
#Mann= 3 , 0 , 0
       0     0.1       0     491   0.045       0     506     0.1       0
Bank Sta=     491,     506
Exp/Cntr=0.3,0.1

Type RM Length L Ch R = 1 ,5745.9,201.354,207.414,210.147
XS GIS Cut Line= 3
     1682251.274      242824.615     1681751.394      242800.729
     1681249.369      242783.797
#Sta/Elev= 30
       0 1160.24    47.6 1151.27   118.9 1136.44   150.4 1128.92   261.5 1100.23
   273.4 1097.65   320.6 1089.87   368.5 1085.01   380.4 1084.32   392.3 1081.72
   404.1 1076.05   456.7 1048.47   475.5 1037.50   487.3 1029.21     493 1027.15
   499.2 1024.76     508 1024.55   511.1 1024.50   569.9 1027.79   606.1 1028.87
   643.7 1030.64   677.4 1033.22   689.3 1034.98   709.0 1040.45   742.0 1052.78
   760.6 1057.95   808.1 1067.96   855.6 1075.13   938.7 1089.36  1002.8 1103.01
#Mann= 3 , 0 , 0
       0     0.1       0     493   0.045       0     508     0.1       0
Bank Sta=     493,     508
Exp/Cntr=0.3,0.1

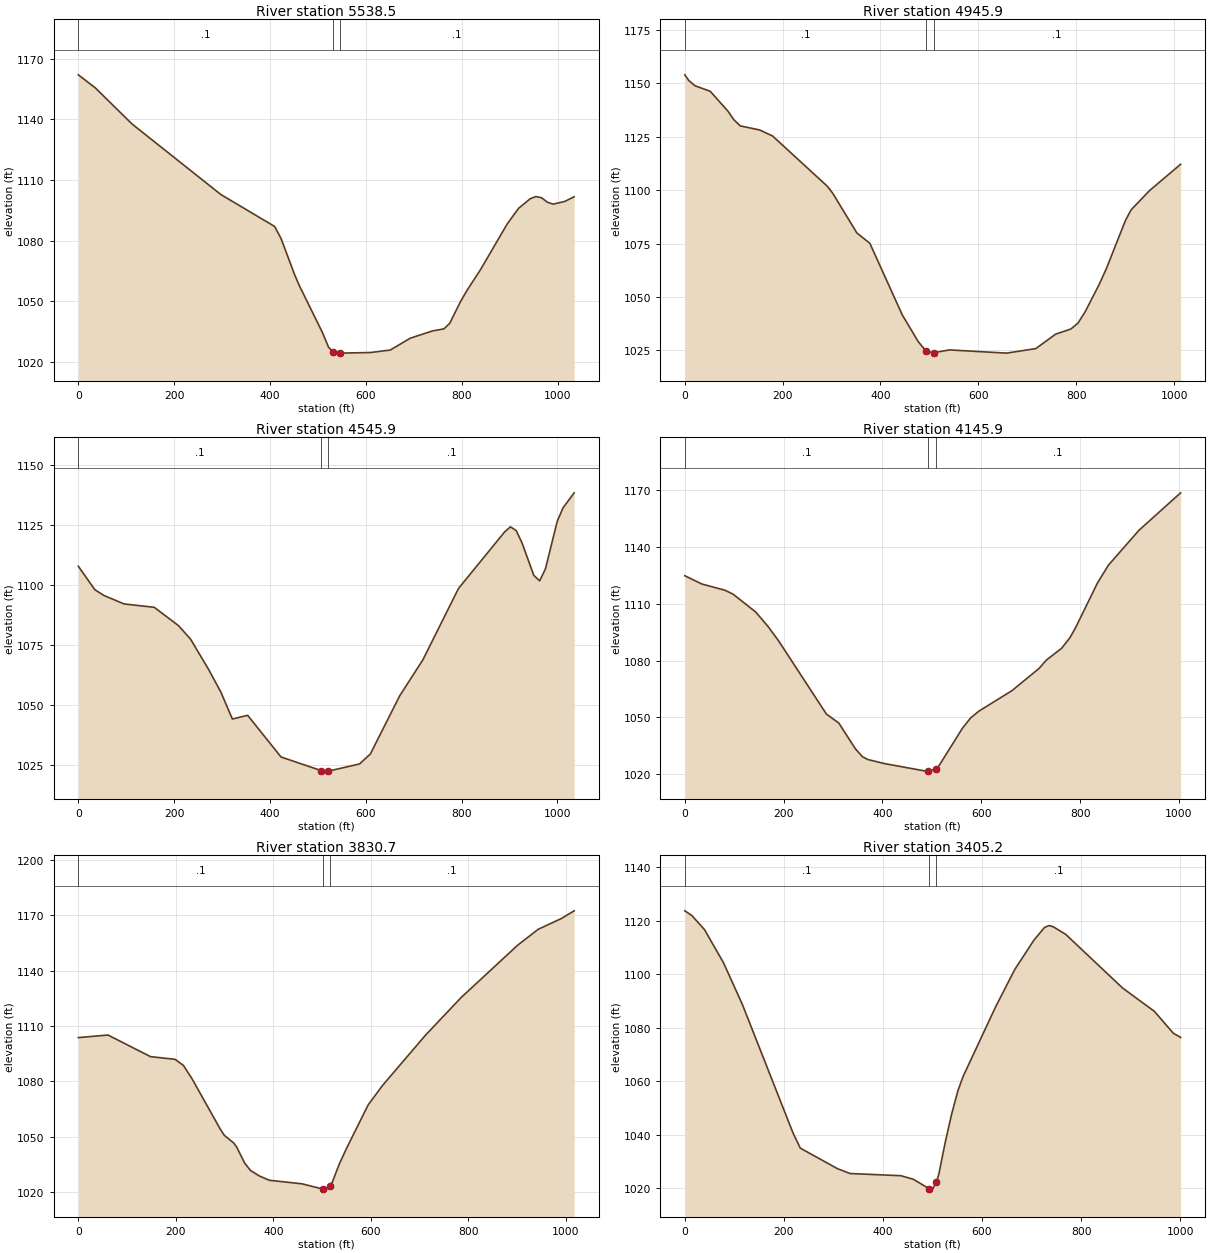
Type RM Length L Ch R = 1 ,5538.5,589.761,592.586,602.763
XS GIS Cut Line= 3
     1682284.767      242763.245     1681773.209      242597.035
     1681281.986      242523.318
#Sta/Elev= 30
       0 1162.13    35.2 1155.71   112.2 1137.74   297.4 1102.80   409.7 1086.95
   423.2 1080.88   451.4 1063.01   460.8 1057.83   509.6 1034.26   522.1 1027.11
   530.9 1024.97   545.9 1024.18   609.1 1024.47   650.9 1025.71   692.6 1031.58
   738.8 1035.17   762.8 1036.20   774.8 1038.88   797.0 1049.51   810.8 1055.20
   838.8 1065.41   894.9 1088.21   918.9 1096.02   942.9 1100.70   954.9 1101.81
   966.9 1101.16   978.9 1098.96   990.9 1098.04  1014.9 1099.36  1034.6 1101.69
#Mann= 3 , 0 , 0
       0     0.1       0   530.9   0.045       0   545.9     0.1       0
Bank Sta=   530.9,   545.9
Exp/Cntr=0.3,0.1

Type RM Length L Ch R = 1 ,4945.9,399.172,400,391.225
XS GIS Cut Line= 3
     1682483.482      242374.039     1682034.232      242151.884
     1681617.577      241853.784
#Sta/Elev= 30
       0 1153.92     8.2 1151.26    20.6 1148.84    52.0 1146.22    88.6 1136.82
   100.1 1132.97   113.4 1130.03   153.1 1128.13   179.6 1125.29   291.3 1101.81
   302.9 1098.36   351.8 1079.94   378.3 1075.13   444.5 1041.65   477.4 1029.07
   493.7 1024.57   508.7 1023.95   540.9 1025.26   657.7 1023.76   717.4 1025.87
   758.2 1032.66   789.1 1035.03   803.7 1037.80   818.3 1043.09   847.5 1056.10
   862.0 1063.45   901.0 1085.95   912.3 1090.77   949.6 1099.71  1013.5 1112.09
#Mann= 3 , 0 , 0
       0     0.1       0   493.7   0.045       0   508.7     0.1       0
Bank Sta=   493.7,   508.7
Exp/Cntr=0.3,0.1

Type RM Length L Ch R = 1 ,4545.9,393.42,400,411.968
XS GIS Cut Line= 3
     1682696.979      241992.401     1682213.211      241816.723
     1681706.109      241699.978
#Sta/Elev= 30
       0 1107.84    34.3 1098.09    52.9 1095.70    95.3 1092.12   158.4 1090.71
   208.9 1083.09   234.2 1077.45   272.1 1064.74   297.4 1055.39   321.6 1044.10
   353.5 1045.64   423.1 1028.26   507.2 1022.56   512.1 1022.36   522.2 1022.37
   587.0 1025.36   609.6 1029.51   670.6 1053.70   719.3 1068.82   793.6 1098.58
   889.9 1122.16   902.0 1124.29   914.2 1122.68   926.4 1117.45   950.8 1104.02
   963.0 1101.74   975.1 1106.76   999.5 1126.47  1011.7 1132.18  1035.0 1138.47
#Mann= 3 , 0 , 0
       0     0.1       0   507.2   0.045       0   522.2     0.1       0
Bank Sta=   507.2,   522.2
Exp/Cntr=0.3,0.1

Type RM Length L Ch R = 1 ,4145.9,316.8,315.194,311.693
XS GIS Cut Line= 3
     1682788.623      241882.059     1682437.609      241526.035
     1682080.277      241171.255
#Sta/Elev= 30
       0 1124.83    34.7 1120.45    81.2 1117.18    97.9 1115.08   143.8 1105.62
   169.0 1097.87   190.4 1090.24   286.5 1051.84   311.7 1047.07   345.3 1033.45
   359.5 1029.31   370.5 1027.81   404.1 1025.66   488.0 1021.68   492.5 1021.69
   507.5 1022.78   514.8 1024.67   561.8 1044.28   578.5 1049.76   595.2 1053.35
   662.2 1064.17   717.0 1075.89   731.5 1080.24   762.6 1086.53   779.3 1092.05
   790.3 1097.09   835.0 1120.90   857.4 1130.42   919.3 1148.86  1003.5 1168.60
#Mann= 3 , 0 , 0
       0     0.1       0   492.5   0.045       0   507.5     0.1       0
Bank Sta=   492.5,   507.5
Exp/Cntr=0.3,0.1

Type RM Length L Ch R = 1 ,3830.7,433.263,425.574,420.021
XS GIS Cut Line= 3
     1683005.614      241671.080     1682662.237      241311.322
     1682241.679      241006.502
#Sta/Elev= 30
       0 1103.69    60.8 1105.09   148.1 1093.38   198.4 1091.93   215.6 1088.60
   232.8 1081.57   290.9 1054.22   299.3 1050.79   318.7 1046.61   324.4 1044.58
   341.2 1035.71   353.1 1031.75   370.3 1028.90   391.6 1026.45   458.8 1024.52
   500.7 1021.73   506.3 1021.65   509.3 1021.67   515.7 1023.55   521.0 1025.55
   534.8 1035.05   550.3 1043.90   594.3 1067.25   623.7 1077.75   711.6 1104.93
   784.9 1125.38   900.4 1153.62   942.9 1162.33   990.2 1168.14  1016.7 1172.34
#Mann= 3 , 0 , 0
       0     0.1       0   500.7   0.045       0   515.7     0.1       0
Bank Sta=   500.7,   515.7
Exp/Cntr=0.3,0.1

Type RM Length L Ch R = 1 ,3405.2,455.377,459.232,463.208
XS GIS Cut Line= 3
     1683297.300      241117.042     1682832.783      240930.697
     1682368.267      240744.351
#Sta/Elev= 30
       0 1123.80    14.1 1122.07    39.7 1116.79    78.0 1104.45   116.5 1088.68
   218.8 1040.61   233.2 1035.08   308.4 1027.38   333.9 1025.58   436.3 1024.77
   461.4 1023.43   493.1 1019.93   500.2 1019.75   508.1 1022.43   513.0 1025.48
   525.8 1037.27   538.6 1047.72   551.4 1056.55   561.8 1061.85   628.2 1088.17
   666.5 1101.97   704.9 1112.85   726.2 1117.57   735.3 1118.29   743.3 1117.90
   768.9 1115.02   884.0 1094.91   948.0 1086.23   986.3 1078.02  1001.0 1076.47
#Mann= 3 , 0 , 0
       0     0.1       0   493.1   0.045       0   508.1     0.1       0
Bank Sta=   493.1,   508.1
Exp/Cntr=0.3,0.1