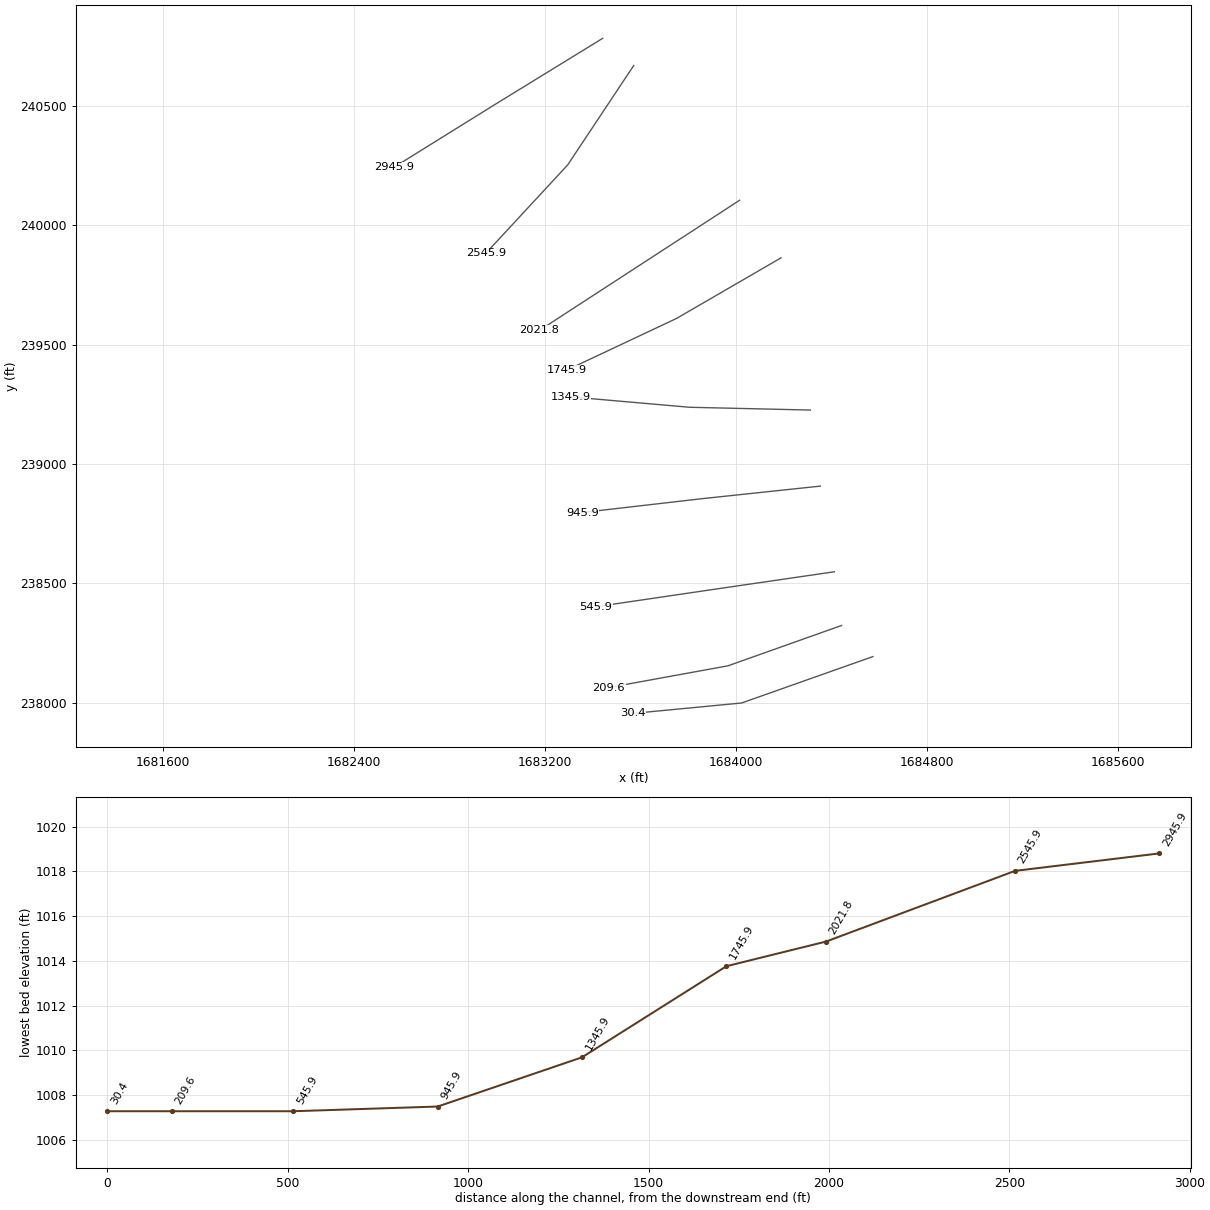
HEC-RAS study RghtFk.prj: RghtFk

--- RghtFk.g01 (geometry) --- (continued)

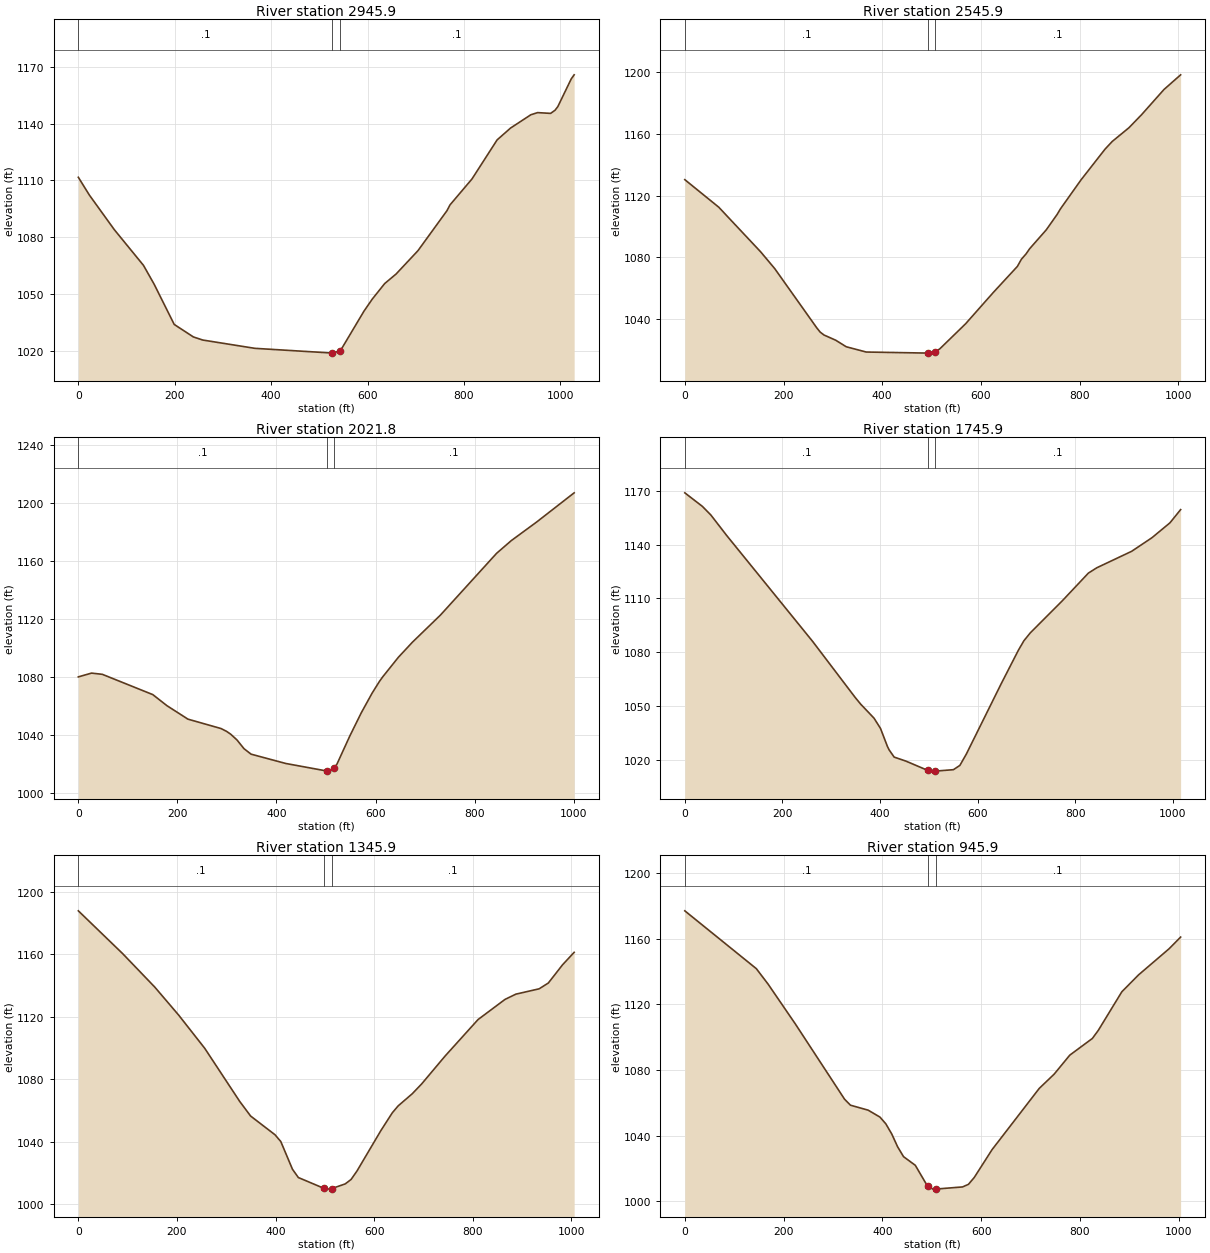
Type RM Length L Ch R = 1 ,2945.9,390.221,400,405.983
XS GIS Cut Line= 3
     1683441.844      240783.954     1682986.476      240504.162
     1682566.793      240243.187
#Sta/Elev= 30
       0 1111.63    22.9 1102.24    74.7 1083.96   135.2 1065.12   157.2 1055.22
   199.0 1033.93   238.7 1027.35   258.1 1025.71   366.2 1021.33     527 1018.84
   530.2 1018.80     542 1020.15   547.4 1021.63   592.5 1040.90   609.8 1047.31
   635.6 1055.52   659.2 1060.55   704.6 1072.87   764.9 1094.02   771.1 1097.04
   816.7 1110.73   868.9 1131.37   896.9 1137.64   938.9 1144.63   952.8 1145.76
   979.9 1145.36   989.1 1147.03   994.8 1148.92  1022.7 1163.59  1028.7 1165.71
#Mann= 3 , 0 , 0
       0     0.1       0     527   0.045       0     542     0.1       0
Bank Sta=     527,     542
Exp/Cntr=0.3,0.1

Type RM Length L Ch R = 1 ,2545.9,533.428,524.171,518.589
XS GIS Cut Line= 3
     1683572.069      240670.010     1683295.219      240253.330
     1682952.609      239883.430
#Sta/Elev= 30
       0 1130.30    68.8 1112.48   153.7 1083.58   182.2 1072.72   267.7 1034.23
   274.3 1031.61   282.0 1029.75   305.7 1026.38   327.1 1022.14   367.5 1018.73
   492.8 1018.04   495.8 1018.02   507.8 1019.07   516.5 1020.75   568.9 1037.02
   624.7 1057.17   673.8 1074.15   681.9 1078.77   691.2 1082.18   698.7 1085.62
   732.3 1097.81   754.1 1107.69   761.1 1111.42   802.7 1130.15   851.2 1149.97
   865.9 1155.01   899.8 1163.90   925.5 1172.38   970.8 1188.65  1004.5 1198.15
#Mann= 3 , 0 , 0
       0     0.1       0   492.8   0.045       0   507.8     0.1       0
Bank Sta=   492.8,   507.8
Exp/Cntr=0.3,0.1

Type RM Length L Ch R = 1 ,2021.8,276.949,275.829,272.749
XS GIS Cut Line= 3
     1684015.824      240105.386     1683596.218      239832.567
     1683176.611      239559.747
#Sta/Elev= 30
       0 1079.94    26.7 1082.55    48.5 1081.70   150.4 1067.69   178.8 1060.08
   221.3 1050.75   288.1 1044.27   299.1 1042.35   307.6 1040.38   320.4 1036.35
   334.5 1030.35   348.7 1026.58   418.7 1020.15   501.4 1014.96   504.5 1014.86
   513.6 1015.72   516.4 1016.97   522.2 1019.76   547.9 1038.98   571.2 1055.12
   593.0 1068.65   608.0 1076.87   614.8 1080.08   646.1 1093.46   674.4 1103.86
   731.1 1122.64   844.4 1165.26   874.0 1174.02   925.5 1186.94  1001.0 1207.04
#Mann= 3 , 0 , 0
       0     0.1       0   501.4   0.045       0   516.4     0.1       0
Bank Sta=   501.4,   516.4
Exp/Cntr=0.3,0.1

Type RM Length L Ch R = 1 ,1745.9,412.474,400,388.036
XS GIS Cut Line= 3
     1684189.413      239864.132     1683752.184      239610.501
     1683290.520      239392.922
#Sta/Elev= 30
       0 1168.79    36.0 1161.25    53.4 1156.43    85.7 1145.07   261.9 1086.02
   348.8 1054.90   360.2 1051.11   387.7 1043.25   400.9 1037.56   415.1 1027.55
   418.3 1025.72   428.9 1021.58   453.0 1019.34     498 1014.14   511.0 1013.76
     513 1013.77   550.3 1014.56   563.5 1016.93   576.9 1023.32   647.8 1062.22
   683.5 1081.14   694.7 1086.37   707.8 1090.78   773.5 1108.67   826.9 1124.09
   844.1 1127.04   915.5 1136.22   957.2 1143.81   994.0 1152.09  1015.8 1159.44
#Mann= 3 , 0 , 0
       0     0.1       0     498   0.045       0     513     0.1       0
Bank Sta=     498,     513
Exp/Cntr=0.3,0.1

Type RM Length L Ch R = 1 ,1345.9,397.04,400,404.618
XS GIS Cut Line= 3
     1684312.116      239226.131     1683806.164      239237.809
     1683308.328      239281.344
#Sta/Elev= 30
       0 1187.86    90.0 1160.43   155.0 1139.06   203.6 1121.08   256.3 1099.90
   327.5 1065.79   349.5 1056.48   398.8 1044.54   410.7 1040.17   434.4 1022.41
   446.3 1017.11   498.6 1010.15   505.7 1009.69   513.6 1010.01   541.4 1013.03
   553.3 1015.89   565.3 1021.31   613.6 1047.10   636.8 1058.50   648.7 1062.96
   677.4 1070.76   696.4 1077.02   744.0 1094.89   810.9 1118.27   865.7 1131.18
   887.6 1134.52   934.7 1137.92   953.4 1141.64   982.4 1153.36  1005.8 1161.29
#Mann= 3 , 0 , 0
       0     0.1       0   498.6   0.045       0   513.6     0.1       0
Bank Sta=   498.6,   513.6
Exp/Cntr=0.3,0.1

Type RM Length L Ch R = 1 ,945.9,399.051,400,400.77
XS GIS Cut Line= 3
     1684353.919      238907.390     1683856.270      238854.512
     1683355.903      238796.727
#Sta/Elev= 30
       0 1176.87   144.9 1141.66   168.4 1132.38   224.2 1107.87   323.6 1062.20
   335.5 1058.57   371.3 1055.55   395.2 1051.34   407.1 1047.24   419.1 1041.05
   431.0 1033.25   443.0 1027.24   466.8 1021.99   490.2 1009.99     493 1009.31
   502.7 1007.49     508 1007.52   562.4 1008.82   574.4 1010.40   586.3 1014.63
   622.2 1031.50   717.8 1068.79   748.0 1077.47   779.6 1089.02   825.4 1099.20
   837.3 1104.08   885.1 1127.62   918.9 1137.88   980.7 1153.77  1004.1 1160.89
#Mann= 3 , 0 , 0
       0     0.1       0     493   0.045       0     508     0.1       0
Bank Sta=     493,     508
Exp/Cntr=0.3,0.1

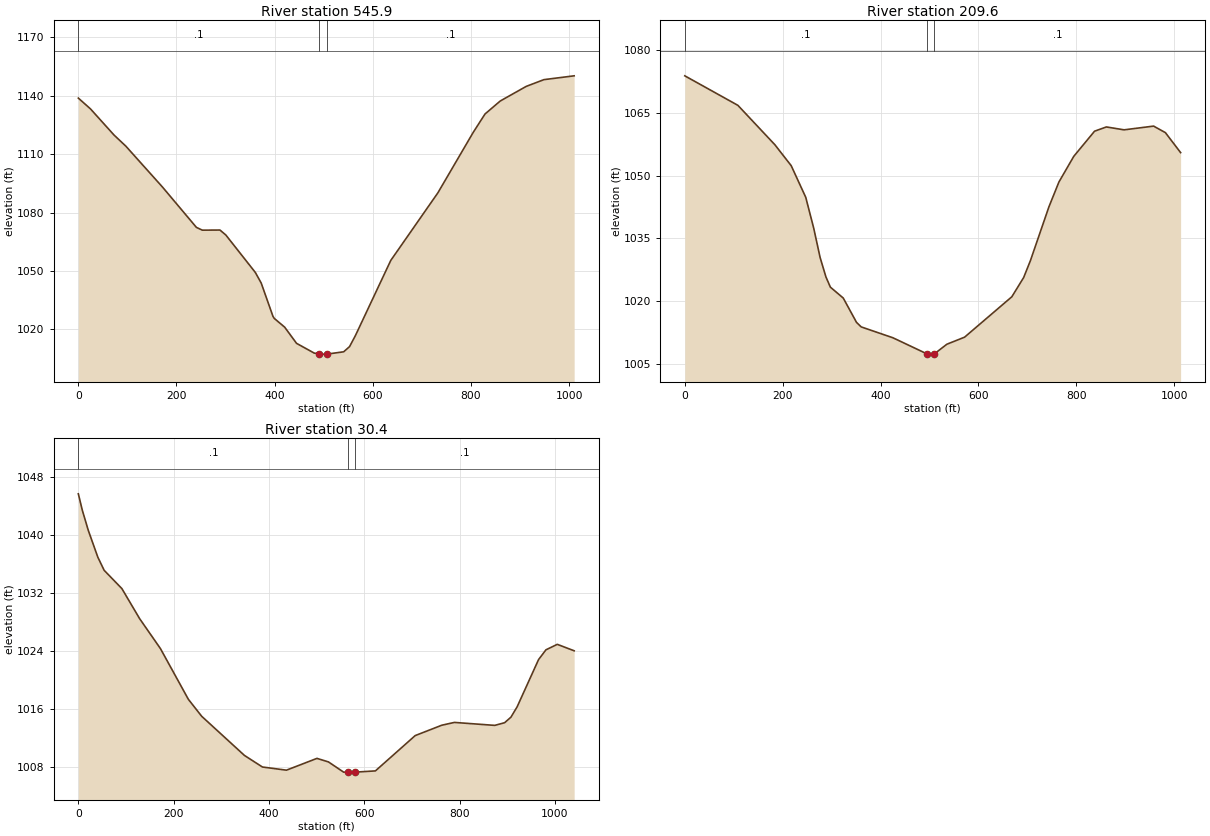
Type RM Length L Ch R = 1 ,545.9,331.74,336.369,337.631
XS GIS Cut Line= 3
     1684412.749      238548.383     1683919.448      238476.427
     1683413.192      238401.890
#Sta/Elev= 30
       0 1138.80    24.7 1133.27    72.7 1119.83    96.7 1114.14   171.4 1093.12
   240.6 1072.38   252.6 1070.96   288.6 1071.02   300.6 1068.45   360.6 1049.25
   372.6 1043.79   396.6 1026.65   399.3 1025.61   420.3 1021.16   444.6 1012.82
   480.6 1007.81     491 1007.37   492.6 1007.28     506 1007.28   540.6 1008.47
   552.6 1011.14   564.6 1016.84   636.6 1055.42   732.6 1090.16   804.6 1121.21
   828.6 1130.64   859.7 1137.32   912.6 1144.82   948.6 1148.28  1010.2 1150.24
#Mann= 3 , 0 , 0
       0     0.1       0     491   0.045       0     506     0.1       0
Bank Sta=     491,     506
Exp/Cntr=0.3,0.1

Type RM Length L Ch R = 1 ,209.6,179.29,179.104,175.639
XS GIS Cut Line= 3
     1684443.095      238323.329     1683967.173      238154.331
     1683467.387      238063.220
#Sta/Elev= 30
       0 1073.86   108.5 1066.80   184.1 1057.37   217.4 1052.37   247.1 1044.81
   263.4 1037.42   276.5 1030.39   288.4 1025.74   297.5 1023.30   323.8 1020.69
   350.9 1014.87   360.5 1013.79   425.3 1011.19     495 1007.33   499.1 1007.28
     510 1007.35   535.5 1009.65   571.7 1011.34   668.3 1021.01   692.4 1025.61
   706.2 1029.65   744.1 1042.55   764.5 1048.47   794.8 1054.60   837.2 1060.61
   861.4 1061.63   897.6 1060.94   957.9 1061.83   982.0 1060.27  1013.1 1055.49
#Mann= 3 , 0 , 0
       0     0.1       0     495   0.045       0     510     0.1       0
Bank Sta=     495,     510
Exp/Cntr=0.3,0.1

Type RM Length L Ch R = 1 ,30.4,24.306,30.45,43.06
XS GIS Cut Line= 3
     1684574.400      238193.009     1684024.052      237998.441
     1683569.538      237954.960
#Sta/Elev= 30
       0 1045.74     8.5 1043.44    21.0 1040.67    41.0 1036.97    54.2 1035.17
    91.4 1032.64   128.6 1028.49   172.2 1024.36   230.9 1017.34   258.8 1015.00
   348.5 1009.59   386.2 1007.99   436.6 1007.55   500.7 1009.18   524.8 1008.69
   556.6 1007.28   566.4 1007.28   581.4 1007.28   623.3 1007.45   706.8 1012.33
   762.5 1013.76   788.9 1014.15   873.8 1013.74   894.4 1014.11   907.6 1014.87
   920.7 1016.31   965.6 1022.83   981.1 1024.18  1004.9 1024.94  1040.3 1024.05
#Mann= 3 , 0 , 0
       0     0.1       0   566.4   0.045       0   581.4     0.1       0
Bank Sta=   566.4,   581.4
Exp/Cntr=0.3,0.1